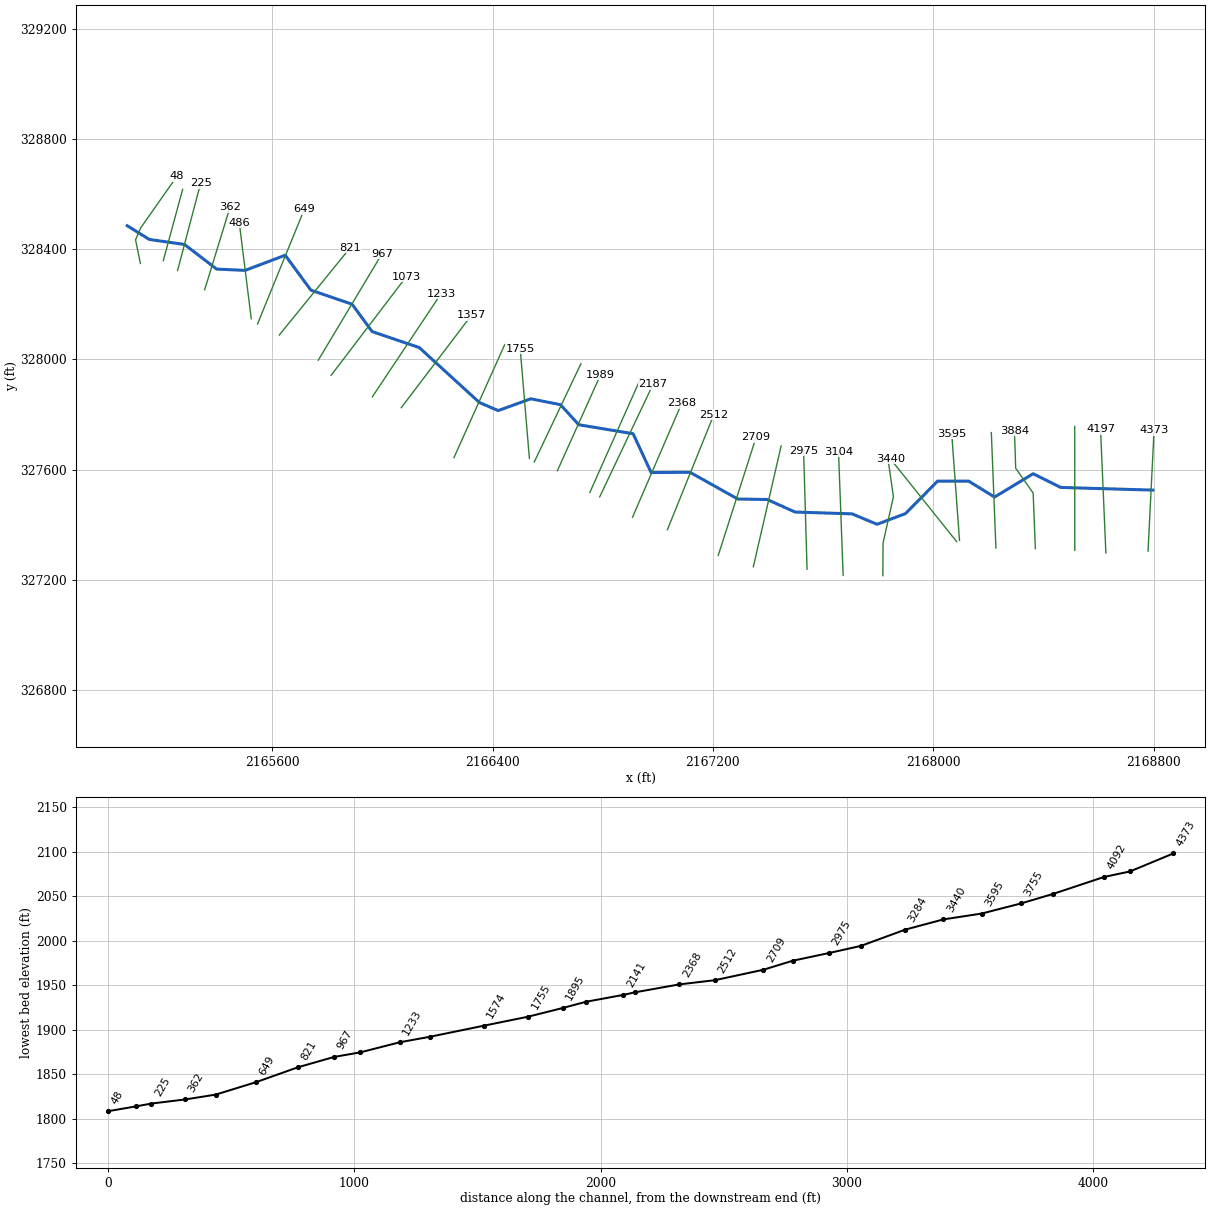
--- LAURELCK2.prj (project) ---

Proj Title=LAURELCK2
Current Plan=p01
Default Exp/Contr=0.3,0.1
English Units
Geom File=g01
Flow File=f01
Plan File=p01
BEGIN DESCRIPTION:
Stream Name- Laurel Creek 2
Flood Zone: Zone A
Greenbrier County, WV
County-Wide Study
WVDHSEM-2018-3, Flood Risk Project
HEC-RAS Version: 5.0.7
General Notes:
For the Hydrology Regression was used.
END DESCRIPTION:
DSS Export Rating Curves= 0
DSS Export Rating Curve Sorted= 0
DSS Export Volume Flow Curves= 0
DXF OffsetX= 0
DXF OffsetY= 0
DXF ScaleX= 0
DXF ScaleY= 0

--- LAURELCK2.p01 (plan) ---

Plan Title=Floodplain
Program Version=5.07
Short Identifier=Floodplain
Geom File=g01
Flow File=f01
Subcritical Flow
K Sum by GR= 0
Std Step Tol= 0.01
Critical Tol= 0.01
Num of Std Step Trials= 20
Max Error Tol= 0.3
Flow Tol Ratio= 0.001
Split Flow NTrial= 30
Split Flow Tol= 0.02
Split Flow Ratio= 0.02
Log Output Level= 0
Friction Slope Method= 1
Unsteady Friction Slope Method= 2
Unsteady Bridges Friction Slope Method= 1
Parabolic Critical Depth
Global Vel Dist= 0 , 0 , 0
Global Log Level= 0
CheckData=True
Encroach Param=-1 ,0,0, 0
Mapping Interval=1HOUR
Computation Time Step Use Courant=        0
Computation Time Step Use Time Series=    0
Computation Time Step Count To Double=0
Computation Time Step Max Doubling=0
Computation Time Step Max Halving=0
Computation Time Step Residence Courant=0
Run HTab= 0
Run UNet= 0
Run Sediment= 0
Run PostProcess= 0
Run WQNet= 0
Run RASMapper=-1
UNET Theta= 0
UNET Theta Warmup= 0
UNET ZTol= 0
UNET ZSATol= 0
UNET MxIter= 0
UNET Max Iter WO Improvement= 0
UNET MaxInSteps= 0
UNET DtIC= 0
UNET DtMin= 0
UNET MaxCRTS= 0
UNET WFStab= 0
UNET SFStab= 0
UNET WFX= 1
UNET SFX= 1
UNET 1D Methodology=Finite Difference
UNET DSS MLevel= 1
UNET Pardiso=0
UNET DZMax Abort= 0
UNET Use Existing IB Tables= 0
UNET Froude Reduction=False
UNET Froude Limit= 0
UNET Froude Power= 0
UNET D1 Cores= 0
UNET D2 Coriolis=0
UNET D2 Cores= 0
UNET D2 Theta= 1
UNET D2 Theta Warmup= 1
UNET D2 Z Tol= 0.01
UNET D2 Volume Tol= 0.01
UNET D2 Max Iterations= 20
UNET D2 Equation= 0
UNET D2 RampUpFraction=0.1
UNET D2 TimeSlices= 1
UNET D2 BCVolumeCheck=0
UNET D1D2 MaxIter= 0
UNET D1D2 ZTol=0.01
UNET D1D2 QTol=0.1
UNET D1D2 MinQTol=1
Write IC File= 0
Write IC File at Fixed DateTime=0
Write IC File at Sim End=0
Echo Input=False
Echo Parameters=False
Echo Output=False
Write Detailed= 0
HDF Write Warmup=0
HDF Write Time Slices=0
HDF Flush=0
HDF Face Node Velocities=0
HDF Compression= 1
HDF Chunk Size= 1
HDF Spatial Parts= 1
HDF Use Max Rows=0
HDF Fixed Rows= 1
Calibration Method= 0
Calibration Iterations= 20
Calibration Max Change=0.05
Calibration Tolerance=0.2
Calibration Maximum=1.5
Calibration Minimum=0.5
Calibration Optimization Method= 1
WQ AD Non Conservative
WQ ULTIMATE=-1
WQ Max Comp Step=1HOUR
WQ Output Interval=15MIN
WQ Output Selected Increments= 0
WQ Output face flow=0
WQ Output face velocity=0
WQ Output face area=0
WQ Output face dispersion=0
WQ Output cell volume=0
WQ Output cell surface area=0
WQ Output cell continuity=0
WQ Output cumulative cell continuity=0
WQ Output face conc=0
WQ Output face dconc_dx=0
WQ Output face courant=0
WQ Output face peclet=0
WQ Output face adv mass=0
WQ Output face disp mass=0
WQ Output cell mass=0
WQ Output cell source sink temp=0
WQ Output nsm pathways=0
WQ Output nsm derived pathways=0
WQ Output MaxMinRange=-1
WQ Daily Max Min Mean=-1
WQ Daily Range=0
WQ Daily Time=0
WQ Create Restart=0
WQ Fixed Restart=0
WQ System Summary=0
WQ Write To DSS=0
WQ Use Fixed Temperature=0
Sorting and Armoring Iterations= 10
XS Update Threshold= 0.02
Bed Roughness Predictor= 0
Hydraulics Update Threshold= 0.02
Energy Slope Method= 1
Volume Change Method= 1
Sediment Retention Method= 0
XS Weighting Method= 0
Number of US Weighted Cross Sections= 1
Number of DS Weighted Cross Sections= 1
Upstream XS Weight=0
Main XS Weight=1
Downstream XS Weight=0
Number of DS XS's Weighted with US Boundary= 1
Upstream Boundary Weight= 1
Weight of XSs Associated with US Boundary= 0
Number of US XS's Weighted with DS Boundary= 1
Downstream Boundary Weight= 0.5
Weight of XSs Associated with DS Boundary= 0.5
Percentile Method= 0
Sediment Output Level= 3
Mass or Volume Output= 0
Output Increment Type= 1
Profile and TS Output Increment= 1
XS Output Flag= 0
XS Output Increment= 10
Write Gradation File= 0
Read Gradation Hotstart= 0
Write HDF5 File= 1
Write Binary Output= 1
Write DSS Sediment File= 0
SV Curve= 0
Specific Gage Flag= 0

--- LAURELCK2.f01 (steady flow) ---

Flow Title=Flow
Program Version=5.07
Number of Profiles= 6
Profile Names=f1p,f10p,f4p,f2p,f02p,f1pplus
River Rch & RM=LAURELCK2,Main            ,4373
     548     289     385     464     766     810
River Rch & RM=LAURELCK2,Main            ,2368
     639     339     450     541     890     945
Boundary for River Rch & Prof#=LAURELCK2,Main            , 1
Up Type= 0
Dn Type= 3
Dn Slope=0.04238
Boundary for River Rch & Prof#=LAURELCK2,Main            , 2
Up Type= 0
Dn Type= 3
Dn Slope=0.04238
Boundary for River Rch & Prof#=LAURELCK2,Main            , 3
Up Type= 0
Dn Type= 3
Dn Slope=0.04238
Boundary for River Rch & Prof#=LAURELCK2,Main            , 4
Up Type= 0
Dn Type= 3
Dn Slope=0.04238
Boundary for River Rch & Prof#=LAURELCK2,Main            , 5
Up Type= 0
Dn Type= 3
Dn Slope=0.04238
Boundary for River Rch & Prof#=LAURELCK2,Main            , 6
Up Type= 0
Dn Type= 3
Dn Slope=0.04238
DSS Import GetInterval= 0
DSS Import GetPeak= 0
DSS Import FillOption= 0

--- LAURELCK2.g01 (geometry) ---

Geom Title=Geometry
Program Version=5.07

River Reach=LAURELCK2       ,Main
Reach XY= 30
     2168797.568      327525.494     2168463.308      327535.142
     2168362.768      327584.911     2168222.707      327500.221
     2168128.673      327558.132     2168015.752      327558.037
     2167899.261      327440.146     2167796.022      327401.317
     2167705.083      327439.263     2167498.151      327445.837
     2167396.925      327491.366     2167290.175      327493.147
     2167116.564      327590.277     2166975.645      327589.215
2166910.13266025327730.299512625     2166712.944      327762.774
     2166646.488      327835.628     2166538.496      327857.091
     2166420.277      327814.187     2166352.105      327843.454
      2166133.81      328042.946     2165962.521      328101.151
     2165889.622      328200.555     2165740.057      328251.589
     2165646.849      328378.421     2165501.326       328323.35
     2165397.948       328328.06     2165281.172      328417.473
     2165153.426      328435.636     2165073.295      328485.571

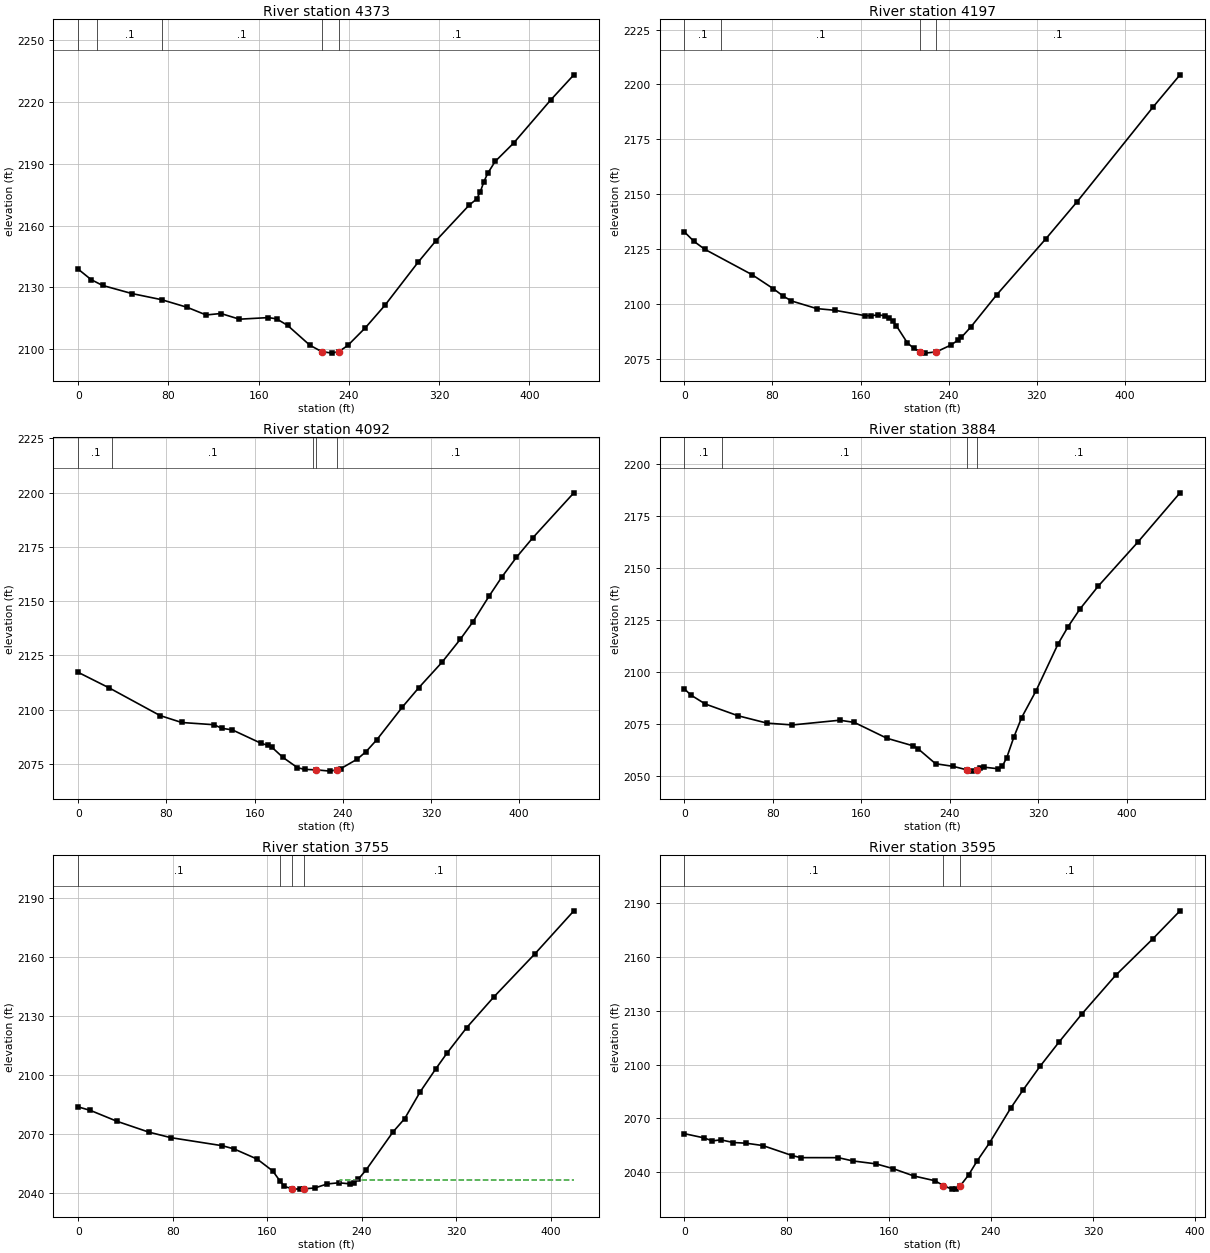
Type RM Length L Ch R = 1 ,4373    ,175.8,176.6,177
XS GIS Cut Line= 2
2168780.07540216327304.1466089812168801.97438156327743.002156026
#Sta/Elev= 30
       0 2138.85    11.5 2133.76    21.6 2130.95    47.7 2126.99    73.9 2124.03
    96.7  2120.3   113.4  2116.6   126.5 2117.31   142.9 2114.55   168.6 2115.32
   175.8 2114.73   185.6 2111.55   205.3 2101.93   215.82098.809     225 2098.06
   231.2 2098.85     239 2101.79   254.6  2110.4   271.9 2121.29   301.2 2142.14
     317 2152.59   346.6 2169.96   353.2 2172.92   356.4 2176.36   359.7 2181.41
     363 2185.39   369.6 2191.17     386 2200.11   418.8 2221.01   439.4 2233.27
#Mann= 5 ,-1 , 0
       0      .1       0   16.73      .1       0   74.17      .1       0
   215.8    .045       0   231.2      .1       0
Bank Sta=215.8,231.2
XS Rating Curve= 0 ,0
Exp/Cntr=0.3,0.1

Type RM Length L Ch R = 1 ,4197    ,104.6,104.8,104.6
XS GIS Cut Line= 2
2168626.96984524327297.2604708812168607.50800235327746.839425762
#Sta/Elev= 30
       0 2132.96     8.6 2128.69    18.4 2125.07    61.6 2113.44    80.8 2107.08
    89.9 2103.69    97.2 2101.54   120.2 2098.05   136.6 2097.28   163.6 2094.88
   169.5 2094.78     176 2095.22   182.6 2094.72   185.9 2093.81   189.2 2092.39
   192.5 2090.22   202.3 2082.58   208.2 2079.96   214.22078.366   218.7 2077.79
   228.8 2078.37   241.7 2081.39   248.3 2083.62   251.6 2085.01   259.9 2089.58
   283.7  2104.4   328.4 2129.93   356.7 2146.75   425.6 2189.79     450  2204.4
#Mann= 4 ,-1 , 0
       0      .1       0   33.33      .1       0   214.2    .045       0
   228.8      .1       0
Bank Sta=214.2,228.8
XS Rating Curve= 0 ,0
Exp/Cntr=0.3,0.1

Type RM Length L Ch R = 1 ,4092    ,204.3,207.7,207.4
XS GIS Cut Line= 2
2168513.96563373327307.0923819322168513.85759677327756.665289317
#Sta/Elev= 30
       0 2117.17    28.3 2109.95    74.2 2097.26    93.9 2094.05   123.4 2093.02
     130 2091.39   139.8 2090.65   166.1 2084.41   172.6 2083.46   175.9 2082.54
   185.7 2077.96   198.9 2073.22   205.4 2072.43     2162072.223   228.4 2071.63
     235 2072.27   238.2 2072.79   253.1 2077.15   261.2 2080.67     271 2086.18
     294 2101.14   308.8 2110.01   330.1 2121.88   346.5 2132.36   358.1 2140.49
   372.7 2152.31   384.3 2161.15   397.4 2170.13   412.1 2179.06   449.6 2199.94
#Mann= 5 ,-1 , 0
       0      .1       0   30.97      .1       0   213.3      .1       0
     216    .045       0     235      .1       0
Bank Sta=216,235
XS Rating Curve= 0 ,0
Exp/Cntr=0.3,0.1

Type RM Length L Ch R = 1 ,3884    ,131.8,129.3,126.1
XS GIS Cut Line= 4
2168370.92102768327313.1811907852168362.80869254327515.026067086
 2168299.4486851 327604.831990672168295.02840424327740.758646808
#Sta/Elev= 30
       0 2092.06     5.8 2089.12    18.9 2084.78    48.5 2079.13    74.7 2075.59
    97.7 2074.72   140.4 2076.99   153.5 2075.95   183.1 2068.31     207 2064.64
     211 2063.36     227 2056.08   243.1 2054.81   255.4 2053.12   260.1 2052.53
   264.8 2053.29   267.2 2054.15   271.2 2054.41   283.3 2053.68   287.3 2054.88
   291.3 2058.96   297.7 2068.81   304.8 2078.27   317.8 2091.13   337.7 2113.66
   346.8 2121.98   357.4 2130.36   373.8 2141.28   409.9 2162.62   447.9 2186.24
#Mann= 4 ,-1 , 0
       0      .1       0   34.17      .1       0   255.4    .045       0
   264.8      .1       0
Bank Sta=255.4,264.8
XS Rating Curve= 0 ,0
Exp/Cntr=0.3,0.1

Type RM Length L Ch R = 1 ,3755    ,157.6,160,159.6
XS GIS Cut Line= 2
2168227.69949933327315.0967239672168211.02973806327734.379766451
#Sta/Elev= 30
       0 2083.69    10.4 2081.89    32.9 2076.36    59.7 2070.89    78.4 2068.06
   122.1 2063.95   131.9 2062.34   151.6 2057.13   164.7 2051.13   170.7 2046.13
   174.6 2043.27     181 2042.11   187.6  2041.9   191.2 2042.07   200.3 2042.48
   210.7 2044.52   220.6 2045.12   230.4 2044.56   233.7 2045.21     237 2046.88
   243.5 2051.48   266.5 2070.97   276.4 2077.74   289.5 2091.35   302.6 2102.93
   312.5 2111.27   328.9    2124   351.9  2139.6   386.6 2161.47   419.6 2183.34
#Mann= 4 ,-1 , 0
       0      .1       0   170.7     .12       0     181    .045       0
   191.2      .1       0
#XS Ineff= 2 , 0
                          221.36         2046.55
Permanent Ineff=
       F       F
Bank Sta=181,191.2
XS Rating Curve= 0 ,0
Exp/Cntr=0.3,0.1

Type RM Length L Ch R = 1 ,3595    ,150.2,155.1,158.8
XS GIS Cut Line= 2
2168095.40412701 327342.992903542168067.17405222327730.189863807
#Sta/Elev= 30
       0 2061.48    15.4 2059.12    21.9 2057.43    28.5 2058.04    38.4 2056.54
    48.3 2056.16    61.4 2054.85    84.4 2049.27      91  2048.1   120.6 2048.08
   131.9 2046.26   150.2 2044.61   163.4 2041.98   179.8 2037.85   196.3 2035.19
   202.9 2032.49   209.4 2030.52   212.7 2030.79     216 2032.27   222.6 2038.41
   229.2 2046.14   239.1 2056.44   255.5 2075.63   265.2 2085.78   278.5    2099
   293.6 2112.76   311.3 2128.27   337.7  2149.8   366.7 2170.09   388.2 2185.87
#Mann= 3 ,-1 , 0
       0      .1       0   202.9    .045       0     216      .1       0
Bank Sta=202.9,216
XS Rating Curve= 0 ,0
Exp/Cntr=0.3,0.1

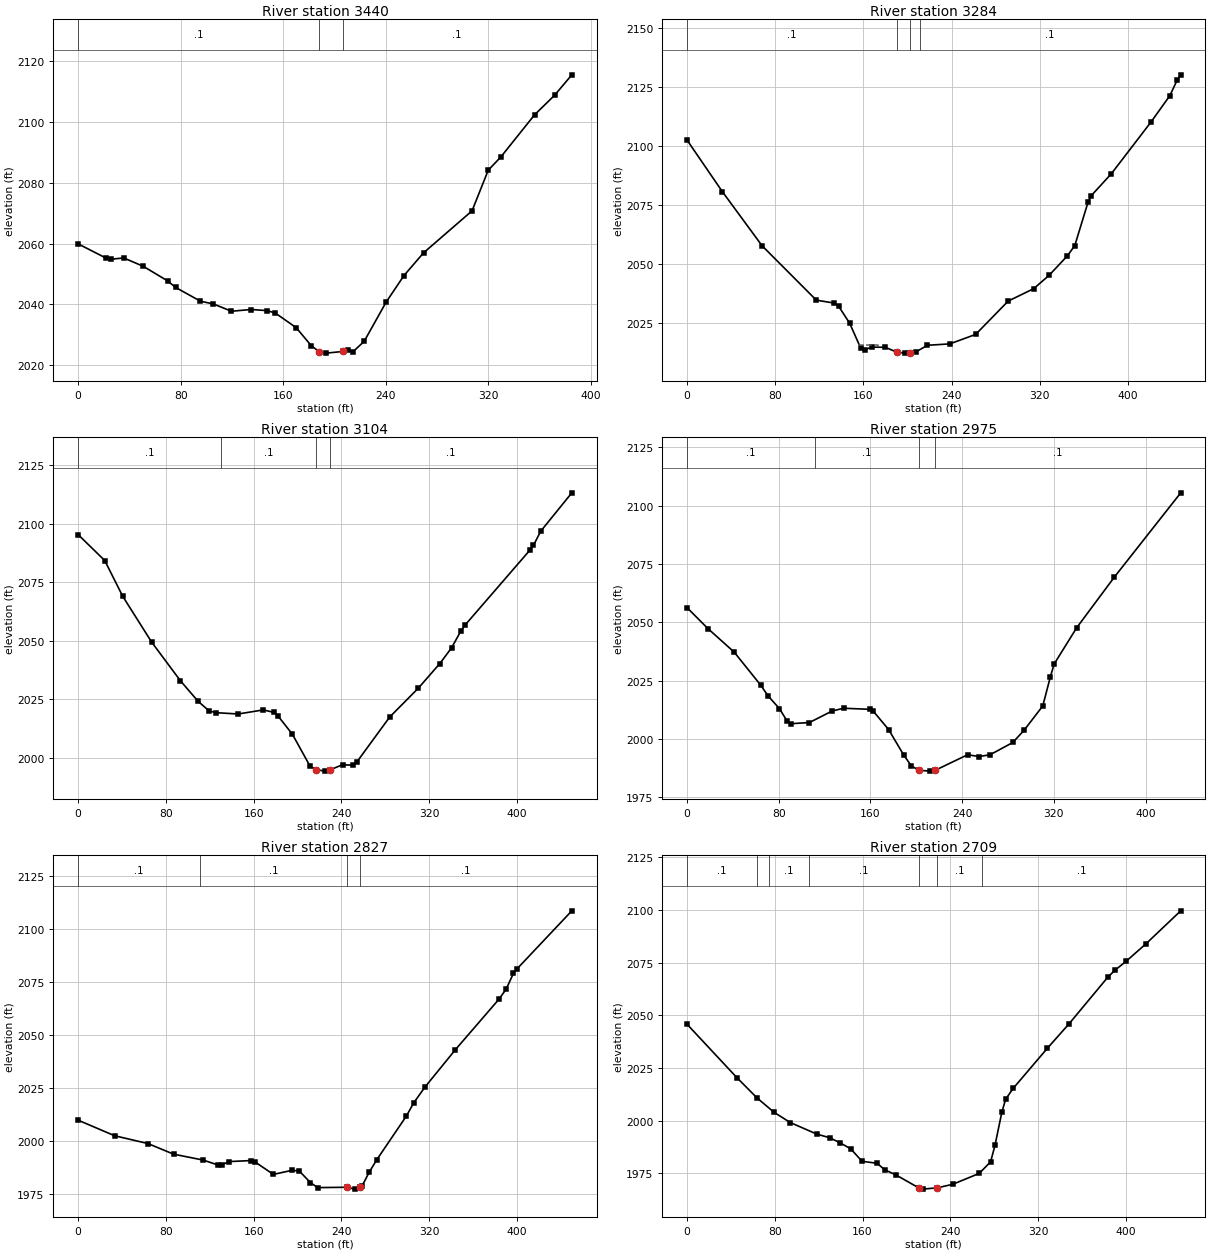
Type RM Length L Ch R = 1 ,3440    ,160,155.3,149.1
XS GIS Cut Line= 2
2168085.08618497 327338.288983272167844.55327767327638.878742795
#Sta/Elev= 30
       0 2059.94    21.4 2055.33    25.6 2054.88    35.6  2055.3    50.9 2052.53
    69.8 2047.75    76.1 2045.59    95.4 2041.07   105.5 2040.16   119.6 2037.77
   134.9 2038.34   147.5 2037.97   153.8 2037.17   170.1 2032.35   181.8 2026.45
   187.9 2024.49   193.5 2023.99   206.3 2024.53   210.5  2024.9   214.5 2024.49
   223.1 2027.89   240.1  2040.7   254.1 2049.51   269.4 2056.99   307.2  2070.8
   319.8 2084.16   329.7 2088.55   355.9 2102.36   371.7 2108.88     385 2115.54
#Mann= 3 ,-1 , 0
       0      .1       0   187.9    .045       0   206.3      .1       0
Bank Sta=187.9,206.3
XS Rating Curve= 0 ,0
Exp/Cntr=0.3,0.1

Type RM Length L Ch R = 1 ,3284    ,177.4,180,181
XS GIS Cut Line= 4
2167817.17705126327214.7641229192167817.80508651327333.093068488
2167855.40684818327501.674299969  2167833.101329327656.789171701
#Sta/Elev= 30
       0 2102.53      32 2080.75    68.1 2057.83   117.3 2034.84   133.1 2033.65
   137.5 2032.29   147.5 2025.12   157.6 2014.52     161  2013.9   167.7    2015
   179.8 2014.92   190.5 2012.84     198 2012.46   202.52012.674     208 2013.07
   218.1 2015.78   238.3 2016.36   261.8 2020.37   291.3 2034.45   314.5 2039.72
   328.5 2045.38   345.1 2053.63   351.7 2057.92   363.7  2076.2   366.6 2078.99
   384.9 2088.29   420.9 2110.17   437.9 2121.26   444.5 2127.79   447.8 2130.08
#Mann= 4 ,-1 , 0
       0      .1       0   190.5    .045       0   202.5      .1       0
   210.9      .1       0
#XS Ineff= 1 ,-1
  154.96  173.38 2015.74
Permanent Ineff=
       F
Bank Sta=190.5,202.5
XS Rating Curve= 0 ,0
Exp/Cntr=0.3,0.1

Type RM Length L Ch R = 1 ,3104    ,129.9,129.8,130
XS GIS Cut Line= 2
2167672.89705021327215.897578751 2167656.0640095327665.582633807
#Sta/Elev= 30
       0 2095.31    24.3  2084.2    40.7  2068.9      67 2049.37    93.3  2032.8
   109.3 2024.07   119.5 2019.89   126.1 2019.17   145.8 2018.62   168.8 2020.36
   178.6  2019.3   181.9 2017.95   195.3 2009.98   211.5 1996.24   216.9 1994.86
   224.6  1994.2   229.6 1994.73     241 1996.94   250.9  1996.7   254.1 1998.14
     284 2017.32     310 2029.61   329.7 2040.18   340.4  2046.9   348.8 2054.04
   352.6 2056.57   411.7 2088.61     415 2090.66   421.6 2096.72     450 2113.15
#Mann= 4 ,-1 , 0
       0      .1       0  130.09      .1       0   216.9    .045       0
   229.6      .1       0
Bank Sta=216.9,229.6
XS Rating Curve= 0 ,0
Exp/Cntr=0.3,0.1

Type RM Length L Ch R = 1 ,2975    ,148.9,147.2,144.7
XS GIS Cut Line= 2
2167541.82178653327238.3902076462167529.20164332327668.765062421
#Sta/Elev= 30
       0 2056.25    18.2 2047.28    41.2 2037.15    64.2 2023.06    70.7 2018.43
    80.6 2012.95    87.2 2007.74    90.4 2006.49   106.8    2007   126.5 2011.92
   136.5 2013.12   159.4 2012.66   162.6 2011.77   175.8 2004.01   188.9 1993.16
   195.5 1988.52     202 1986.55   211.9 1986.17   216.31986.486   244.7 1993.19
   254.8 1992.42   264.4  1993.2   284.1 1998.44   293.9 2003.63   310.3 2014.12
   316.9 2026.59   320.2 2032.07   339.9 2047.65   372.7 2069.32   430.6 2105.44
#Mann= 4 ,-1 , 0
       0      .1       0  111.77      .1       0     202    .045       0
   216.3      .1       0
Bank Sta=202,216.3
XS Rating Curve= 0 ,0
Exp/Cntr=0.3,0.1

Type RM Length L Ch R = 1 ,2827    ,119,118.2,116.2
XS GIS Cut Line= 2
2167346.77911705327247.1694145622167447.63551693327685.721562661
#Sta/Elev= 30
       0 2010.02    33.3 2002.68    63.6 1999.01    87.1 1993.99     114 1991.22
   127.5  1988.9   130.9 1988.99   137.6 1990.51   157.8 1990.99   161.2 1990.36
     178 1984.46   194.8 1986.38   201.6 1986.07   211.7 1980.62   218.4 1978.25
   245.3 1978.41   252.1 1977.53   256.91978.301   258.8 1978.99   265.5 1985.68
   272.3 1991.44   299.2 2011.95   305.9 2018.18     316 2025.52   343.7 2043.12
   383.4  2066.9   390.1 2071.71   396.8 2079.21   400.2 2081.39     450 2108.65
#Mann= 4 ,-1 , 0
       0      .1       0  111.21      .1       0   245.3    .045       0
   256.9      .1       0
Bank Sta=245.3,256.9
XS Rating Curve= 0 ,0
Exp/Cntr=0.3,0.1

Type RM Length L Ch R = 1 ,2709    ,197.1,196.9,195.2
XS GIS Cut Line= 2
2167219.30189633327288.4255585762167356.66795206327716.946931127
#Sta/Elev= 30
       0 2045.74    45.4 2020.41    63.7  2010.8    79.4 2003.89    94.1 1999.07
   118.2 1993.59   130.2 1991.82   139.4 1989.46   149.2  1986.6   159.5 1980.68
   173.3 1979.71   180.2 1976.63   190.5 1974.17   211.2 1968.06   214.7 1967.45
   228.1 1968.07   242.2 1969.74   266.3  1974.9   276.7  1980.4   280.7 1988.21
     287 2004.08   290.4  2010.1   297.3 2015.28   328.3 2034.23   348.1 2045.86
   383.5 2068.03   389.8 2071.25   400.3 2075.64   418.5    2084     450 2099.56
#Mann= 7 ,-1 , 0
       0      .1       0   64.21      .1       0   74.91      .1       0
  110.83      .1       0   211.2    .045       0   228.1      .1       0
  269.27      .1       0
Bank Sta=211.2,228.1
XS Rating Curve= 0 ,0
Exp/Cntr=0.3,0.1

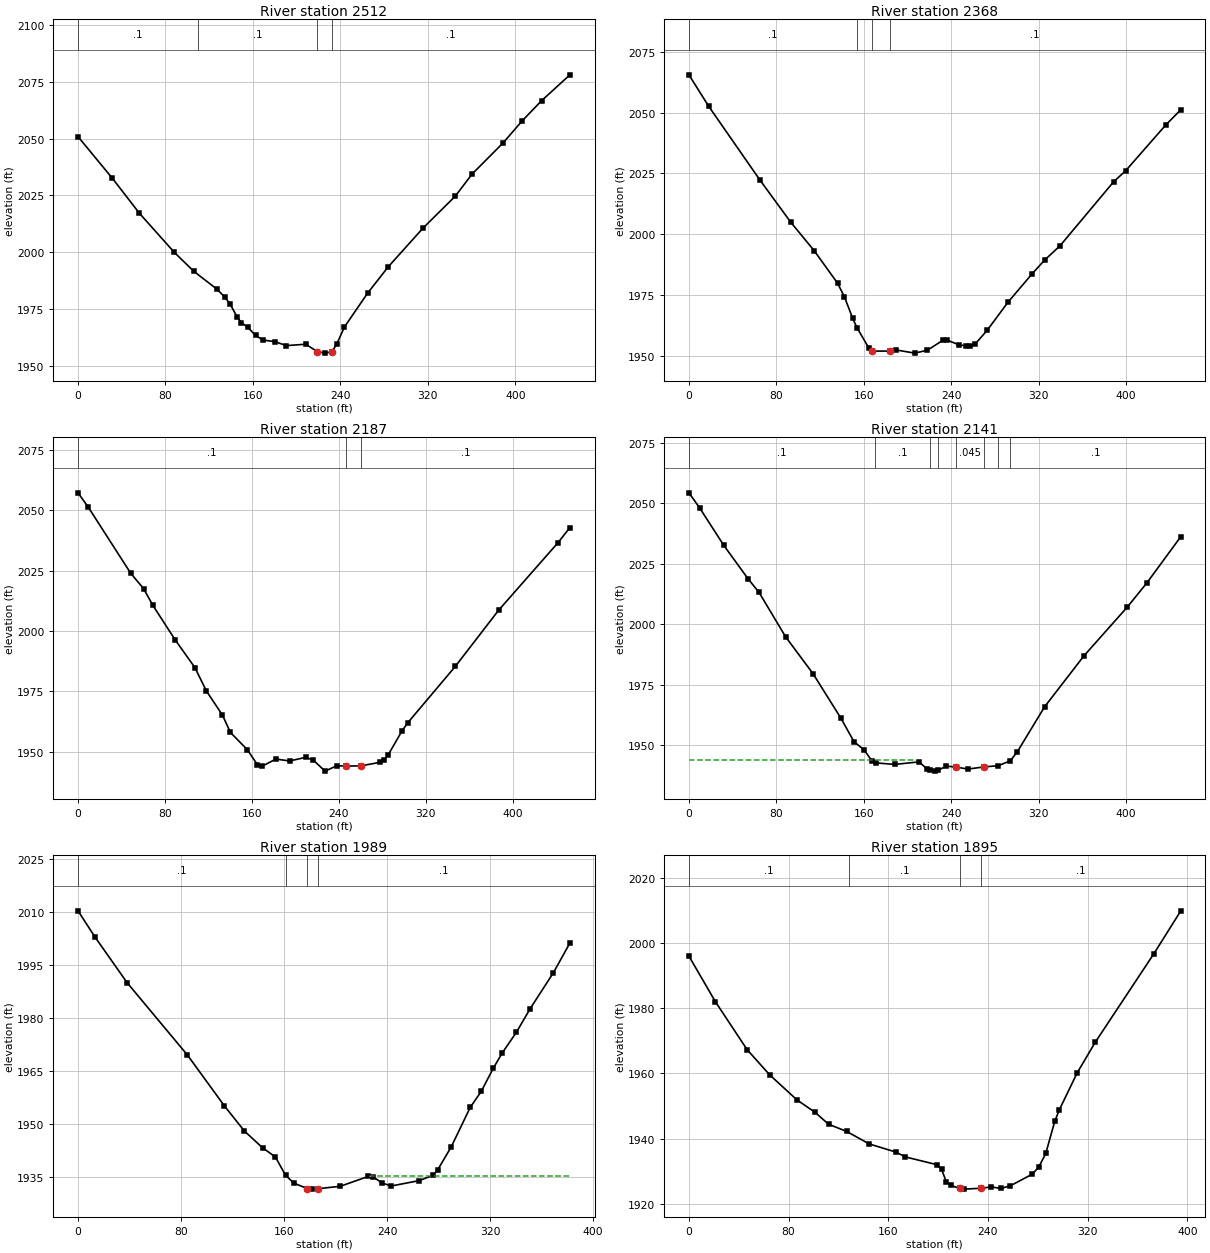
Type RM Length L Ch R = 1 ,2512    ,145.8,144.4,143.9
XS GIS Cut Line= 2
2167034.72539657327381.6443161722167203.12515325327798.946990442
#Sta/Elev= 30
       0 2050.83    31.5 2032.49    56.2 2017.15    88.1    2000   105.7 1991.76
   126.7 1983.96   134.3 1980.36   139.3 1977.15   145.4 1971.75   149.4 1969.09
   155.3 1967.11   162.4 1963.49   169.4 1961.46     180 1960.77   190.7 1959.04
   208.3 1959.63     219 1956.38     226 1955.73   232.21956.349   236.6 1959.58
   243.7 1967.19     265 1982.12   283.8 1993.64   315.7 2010.69   345.2 2024.71
   360.5 2034.38   388.8 2048.04   406.5 2057.84   424.1 2066.62     450 2077.98
#Mann= 4 ,-1 , 0
       0      .1       0   110.2      .1       0     219    .045       0
   232.2      .1       0
Bank Sta=219,232.2
XS Rating Curve= 0 ,0
Exp/Cntr=0.3,0.1

Type RM Length L Ch R = 1 ,2368    ,177.1,181,181.2
XS GIS Cut Line= 2
2166908.10112622327427.059744411 2167086.5488109327840.165570845
#Sta/Elev= 30
       0  2065.5      18 2052.61    64.9 2022.25    93.1 2004.89   114.5 1993.19
     136 1979.76   142.3 1974.13   149.8 1965.31   153.8 1961.41   164.6  1953.1
   167.61951.826   183.6 1951.85   189.6  1952.3   206.6    1951   218.2 1952.21
   232.5 1956.33     236 1956.39   247.1 1954.41   253.9 1953.95   257.5 1953.84
   262.1 1954.87   272.8 1960.37     292 1972.01   314.1  1983.7   325.4 1989.28
   339.5 1995.17   388.6 2021.53   399.4 2025.97   436.2 2044.86     450 2051.14
#Mann= 4 ,-1 , 0
       0      .1       0  153.32      .1       0   167.6    .045       0
   183.6      .1       0
#XS Ineff= 2 , 0
                          232.74         1956.13
Permanent Ineff=
       F       F
Bank Sta=167.6,183.6
XS Rating Curve= 0 ,0
Exp/Cntr=0.3,0.1

Type RM Length L Ch R = 1 ,2187    ,45.6,46.3,46.3
XS GIS Cut Line= 2
2166788.78846396327500.6848660932166982.50326483327909.580161978
#Sta/Elev= 30
       0 2057.14     9.5 2051.17    48.5 2023.86    60.3 2017.54    68.8 2010.65
    89.3 1996.38   107.5 1984.89   118.1  1975.2   132.9  1965.2   140.2 1958.05
   155.8 1950.89   164.9 1944.78   169.2 1944.06   182.1 1947.04   194.6 1946.25
   209.5 1947.75   216.4  1946.6   227.3 1942.05   238.2  1944.3   246.2 1944.12
     260 1944.23   278.1  1945.7   281.7 1946.76   285.4 1948.82   297.9 1958.58
   303.5 1962.14   347.1 1985.36     387 2008.63   441.5 2036.49   452.5 2042.78
#Mann= 3 , 0 , 0
       0      .1       0   246.2    .045       0     260      .1       0
#XS Ineff= 2 , 0
          210.03 1947.62
Permanent Ineff=
       F       F
Bank Sta=246.2,260
XS Rating Curve= 0 ,0
Exp/Cntr(USF)=0,0
Exp/Cntr=0.3,0.1

Type RM Length L Ch R = 1 ,2141    ,149.7,151.6,156.4
XS GIS Cut Line= 2
2166753.12198831327517.0430605342166936.14923513327928.140405359
#Sta/Elev= 30
       0 2054.21     9.7 2048.05    31.9  2032.5    54.2 2018.63    64.2 2013.03
    88.4 1994.75   113.6 1979.44   138.8 1961.26   151.1 1951.34   160.2 1948.04
   167.4 1943.46     171 1942.62   188.4    1942   210.5 1943.04   217.7 1940.19
   220.7 1939.69   224.9 1939.22   228.2 1939.67   235.6 1941.28   244.2 1940.93
   255.1 1940.07   270.31940.974   282.9 1941.46     294 1943.48   300.5 1947.26
   325.4 1965.81   361.4 1986.87   400.9 2006.94   418.8 2016.91     450  2036.1
#Mann= 8 ,-1 , 0
       0      .1       0  170.16      .1       0   220.7      .1       0
   228.2      .1       0   244.2    .045       0   270.3      .1       0
   282.9     .12       0     294      .1       0
#XS Ineff= 2 , 0
          206.82 1943.87
Permanent Ineff=
       F       F
Bank Sta=244.2,270.3
XS Rating Curve= 0 ,0
Exp/Cntr=0.3,0.1

Type RM Length L Ch R = 1 ,1989    ,92.1,94.4,96.5
XS GIS Cut Line= 2
 2166635.1917337327595.7876445232166791.86357264327944.182090892
#Sta/Elev= 30
       0 2010.42      13 2003.09    38.2    1990      85  1969.5   113.7 1955.08
   129.2 1947.97   143.3 1943.21   153.3  1940.6   161.2 1935.39   167.7 1933.17
   178.1 1931.63   182.1 1931.48   186.1 1931.59   203.7 1932.29   225.3 1935.07
   228.9 1935.02   236.1 1933.23   243.2 1932.37   264.8 1933.88   275.6 1935.38
   279.2 1936.88   289.8 1943.44   304.6 1954.67   313.2 1959.23   322.4 1965.71
   329.6 1970.19   340.4 1975.94   351.2 1982.71   369.2 1992.87     382  2001.3
#Mann= 4 ,-1 , 0
       0      .1       0   161.2     .12       0   178.1    .045       0
   186.1      .1       0
#XS Ineff= 2 , 0
                           226.9          1935.1
Permanent Ineff=
       F       F
Bank Sta=178.1,186.1
XS Rating Curve= 0 ,0
Exp/Cntr=0.3,0.1

Type RM Length L Ch R = 1 ,1895    ,133.9,139.4,142
XS GIS Cut Line= 2
2166551.41004515327627.8241131272166720.73427545327984.488062434
#Sta/Elev= 30
       0 1995.97    21.3 1981.96    46.7 1967.29    64.8 1959.56    86.6 1951.91
   101.2 1948.07   112.1 1944.41   126.6  1942.2   144.7 1938.37   166.3 1935.85
   173.7 1934.39   199.2 1931.99   202.8 1930.57   206.5 1926.82   210.1 1925.64
   217.4 1924.74     221 1924.51   234.8 1924.79   242.8  1925.2   250.1 1924.72
   257.7 1925.48   275.5 1929.08   280.7 1931.23   286.4 1935.44   293.6 1945.29
   297.3 1948.85   311.6 1960.16   326.3 1969.66   373.2 1996.72   394.8 2009.86
#Mann= 4 ,-1 , 0
       0      .1       0  128.69      .1       0   217.4    .045       0
   234.8      .1       0
Bank Sta=217.4,234.8
XS Rating Curve= 0 ,0
Exp/Cntr=0.3,0.1

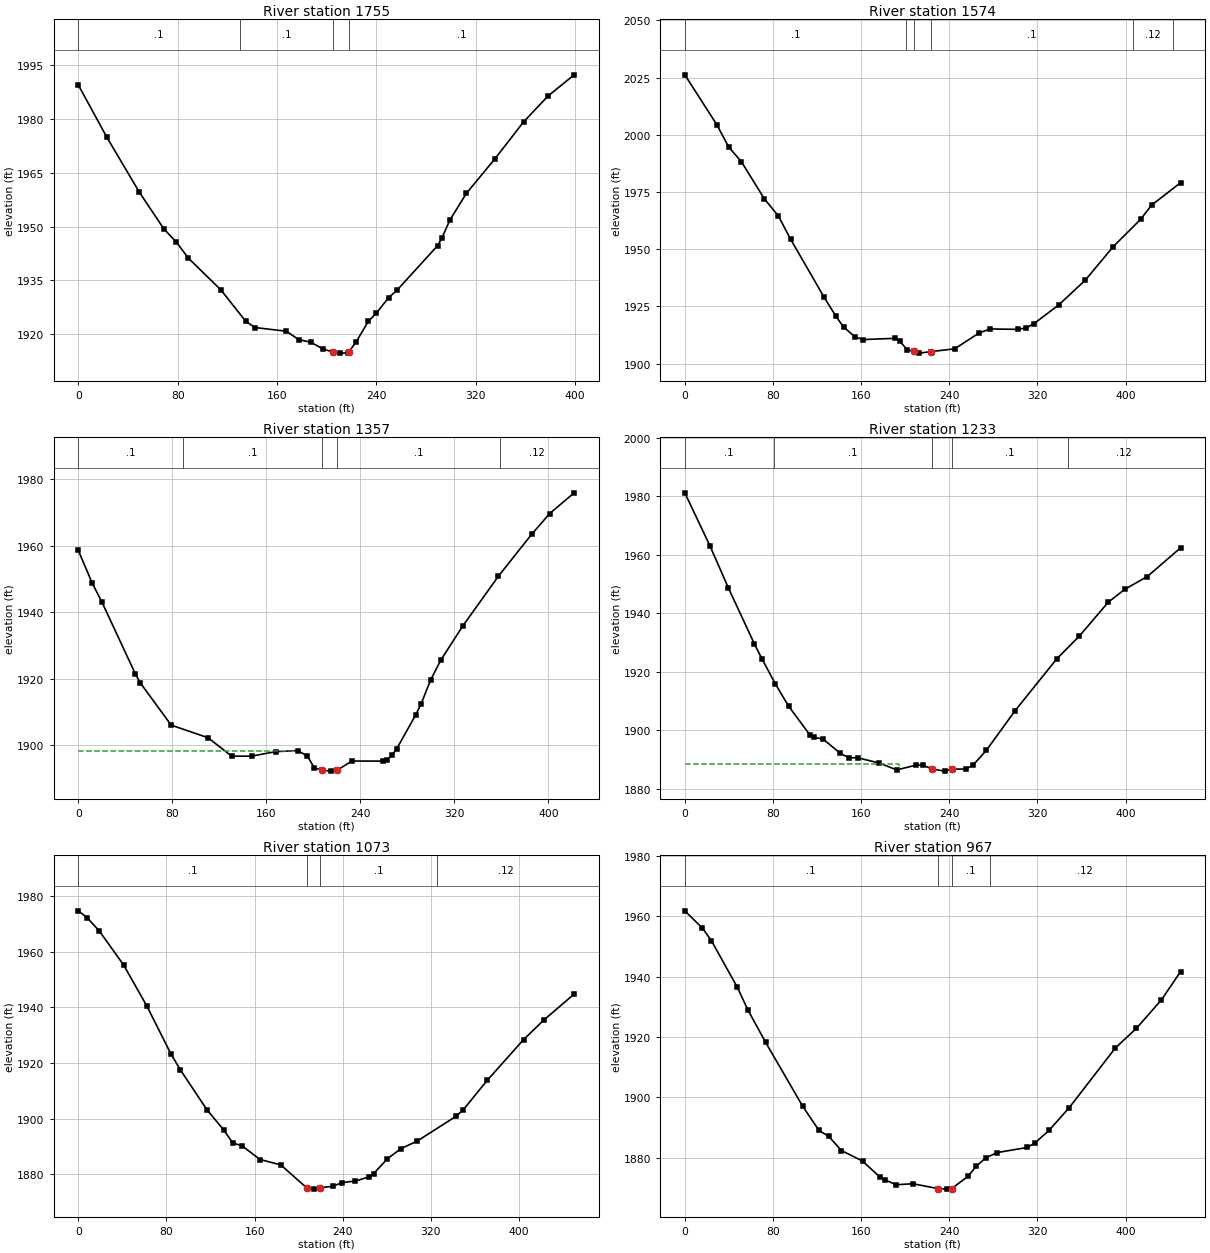
Type RM Length L Ch R = 1 ,1755    ,187.7,181.7,180.1
XS GIS Cut Line= 2
2166533.53252349327640.727541198 2166500.1455912328038.694698391
#Sta/Elev= 30
       0 1989.35    22.8 1974.93    49.1 1959.57    68.9 1949.33    78.8 1945.75
    88.6 1941.21   114.8  1932.4   134.7 1923.72   142.1 1921.92   167.6 1920.89
   177.5 1918.56   187.4 1917.81   197.3 1915.91   205.21915.125   210.5  1914.8
     217 1914.86     218 1915.25   223.6 1917.79   233.5 1923.61   240.1 1925.93
     250 1930.25   256.5 1932.22   289.5 1944.72   292.8 1946.79   299.3  1951.8
   312.5 1959.19   335.6 1968.84   358.6 1979.07   378.4  1986.3   399.4 1992.18
#Mann= 4 ,-1 , 0
       0      .1       0  130.06      .1       0   205.2    .045       0
     218      .1       0
Bank Sta=205.2,218
XS Rating Curve= 0 ,0
Exp/Cntr=0.3,0.1

Type RM Length L Ch R = 1 ,1574    ,220.4,216.5,216.5
XS GIS Cut Line= 2
2166259.70955131327643.5061104742166444.06979608328054.007389582
#Sta/Elev= 30
       0 2026.17      29 2004.45    39.8 1994.65    51.3 1988.25    72.2    1972
    84.9 1964.52      96 1954.38   126.1 1929.28   136.9 1920.86   144.1 1915.97
   154.9 1911.55   162.1 1910.52   190.9 1911.05   195.3 1909.72   201.7 1906.16
   207.61905.314     213 1904.59   223.3 1905.25   244.9 1906.47   267.2 1913.42
   277.2 1915.16   302.4 1914.97   309.6 1915.59   316.8 1917.44   339.2 1925.58
   363.5 1936.47   388.8  1951.1   413.7 1963.05   423.6 1969.21     450 1979.07
#Mann= 6 ,-1 , 0
       0      .1       0  200.96      .1       0   207.6    .045       0
   223.3      .1       0  406.96     .12       0  442.91      .1       0
Bank Sta=207.6,223.3
XS Rating Curve= 0 ,0
Exp/Cntr=0.3,0.1

Type RM Length L Ch R = 1 ,1357    ,123.8,124,124.3
XS GIS Cut Line= 2
2166068.36410931327824.7833008272166323.50035544328160.912036875
#Sta/Elev= 30
       0 1958.52    11.6 1948.87    19.9 1943.14    48.6 1921.41    52.8 1918.73
      79 1906.08   110.5 1902.27   130.5 1896.74   147.5 1896.76   168.1 1898.12
   186.7 1898.42   194.9 1896.81   200.8 1893.27   207.8 1892.53   214.8 1892.26
   220.5  1892.6   232.9 1895.29   259.3 1895.27   262.9 1895.67     267 1897.05
   270.9 1898.92   287.2 1909.18   291.7 1912.41   299.9 1919.68   308.5  1925.6
   327.2 1935.84   357.6 1950.82   385.7 1963.31   401.1 1969.57     422 1975.82
#Mann= 5 ,-1 , 0
       0      .1       0   88.93      .1       0   207.8    .045       0
   220.5      .1       0  358.81     .12       0
#XS Ineff= 2 , 0
          183.15 1898.44
Permanent Ineff=
       F       F
Bank Sta=207.8,220.5
XS Rating Curve= 0 ,0
Exp/Cntr=0.3,0.1

Type RM Length L Ch R = 1 ,1233    ,159.5,159.8,160.4
XS GIS Cut Line= 2
2165963.38110357327864.2209831872166212.76271663328238.799160698
#Sta/Elev= 30
       0 1981.21    22.9 1963.02    39.6 1948.65    63.2 1929.51    70.3 1924.24
    82.1 1915.92    94.2 1908.26   113.5 1898.43   117.5 1897.54   125.3 1897.05
   141.3 1892.06     149  1890.6   156.9 1890.59   176.6 1888.79   192.3 1886.44
   209.9 1888.08     216 1888.07   224.5 1886.74   235.7 1886.03   242.2 1886.71
   255.4 1886.75     262 1888.25   273.8  1893.2   299.8 1906.72   337.7 1924.48
   357.9 1932.14   384.3 1943.79   399.5 1948.26   419.8 1952.59     450 1962.41
#Mann= 5 ,-1 , 0
       0      .1       0   80.59      .1       0   224.5    .045       0
   242.2      .1       0  347.47     .12       0
#XS Ineff= 2 , 0
          194.44 1888.45
Permanent Ineff=
       F       F
Bank Sta=224.5,242.2
XS Rating Curve= 0 ,0
Exp/Cntr=0.3,0.1

Type RM Length L Ch R = 1 ,1073    ,104.6,106,106.7
XS GIS Cut Line= 2
2165813.67387078327942.4375632022166086.51214605328300.291270115
#Sta/Elev= 30
       0 1974.66     8.1 1972.15    19.2 1967.34    41.1 1955.21    62.1 1940.53
    84.1 1923.23    92.5 1917.62   116.6 1903.27   131.9 1895.99   140.1 1891.31
   148.7 1890.22   164.9 1885.34   183.8 1883.39   207.2 1875.18     214  1874.7
   218.9 1875.18   230.9 1875.73   239.1 1877.01   251.5 1877.62   263.9  1879.1
   268.1 1880.31   280.4 1885.56   292.8 1889.24   307.8 1892.01     343 1900.92
   349.3 1903.17   371.1 1913.77   404.1 1928.42   422.5 1935.44     450 1944.76
#Mann= 4 ,-1 , 0
       0      .1       0   207.2    .045       0   218.9      .1       0
  325.68     .12       0
Bank Sta=207.2,218.9
XS Rating Curve= 0 ,0
Exp/Cntr=0.3,0.1

Type RM Length L Ch R = 1 ,967     ,147.3,146.4,145.2
XS GIS Cut Line= 2
2165767.02091106327997.5368606672165998.29609419328383.557313061
#Sta/Elev= 30
       0 1961.82    15.9 1956.13    24.1 1951.96    47.7 1936.46    57.2 1929.02
    73.3 1918.26     107 1897.06   121.8 1889.02   130.7 1887.07   142.1 1882.39
   161.3 1878.89   176.8 1873.68   181.6 1872.66   191.9 1871.05   207.2 1871.37
   229.4 1869.79   237.8 1869.59   242.3 1869.79   256.9  1873.8   264.5 1877.13
     273 1879.94   283.7 1881.72   310.8 1883.39   318.1 1884.99   330.5 1889.03
     349 1896.63   390.7 1916.35   409.9 1922.88   432.6 1932.32     450 1941.71
#Mann= 4 ,-1 , 0
       0      .1       0   229.4    .045       0   242.3      .1       0
  276.99     .12       0
Bank Sta=229.4,242.3
XS Rating Curve= 0 ,0
Exp/Cntr=0.3,0.1

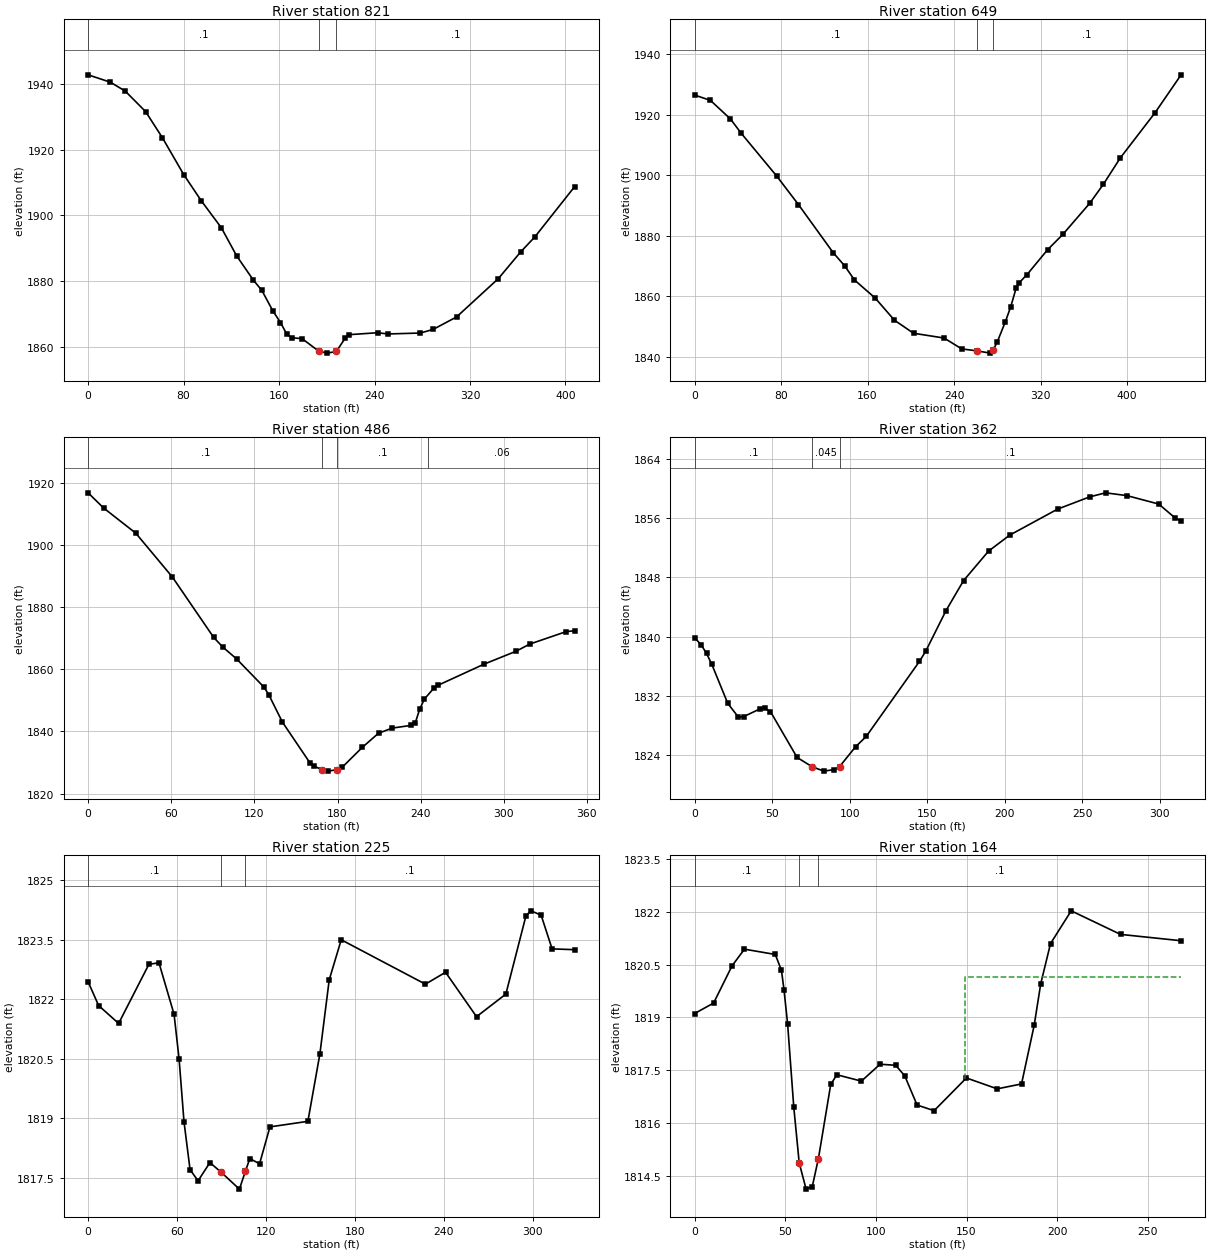
Type RM Length L Ch R = 1 ,821     ,169.5,172.1,174.4
XS GIS Cut Line= 2
 2165625.2417775328088.5939556372165882.37854364328404.985644488
#Sta/Elev= 30
       0 1942.74    18.6  1940.5    31.1 1937.79    48.2 1931.54    62.3 1923.57
    80.2 1912.33    94.7 1904.48   111.7 1896.17   124.5 1887.62   138.5 1880.25
   145.6 1877.12   154.8 1870.91   161.2 1867.36   166.6 1863.73   170.8 1862.71
   179.3 1862.45   193.51858.572   200.4 1858.04     208 1858.56   215.5 1862.62
   218.4 1863.65   242.7 1864.25   251.2 1863.87   278.5 1864.16   289.2 1865.27
   308.8 1869.06   343.8 1880.73   362.4 1888.81   374.5 1893.47   407.7 1908.71
#Mann= 3 ,-1 , 0
       0      .1       0   193.5    .045       0     208      .1       0
Bank Sta=193.5,208
XS Rating Curve= 0 ,0
Exp/Cntr=0.3,0.1

Type RM Length L Ch R = 1 ,649     ,158.5,163.1,168
XS GIS Cut Line= 2
2165546.34363327328128.8244993522165716.31464519328545.489658812
#Sta/Elev= 30
       0 1926.45    14.7 1924.67    33.2 1918.53      43 1913.86      76 1899.64
    96.1 1890.22   128.1 1874.38   138.9 1869.94   147.9  1865.3   167.1 1859.31
   184.8 1852.02   202.5 1847.69   230.8 1846.11   247.1 1842.51   260.9 1841.89
   273.4 1841.12     276 1842.05   279.8 1844.68   287.4 1851.44   292.4 1856.42
   297.4 1862.59   299.9 1864.25   307.5 1867.09   326.5  1875.3   340.7  1880.4
   365.5 1890.67     378 1896.88   393.8 1905.67   425.8 1920.55     450 1933.13
#Mann= 3 ,-1 , 0
       0      .1       0   260.9    .045       0     276      .1       0
Bank Sta=260.9,276
XS Rating Curve= 0 ,0
Exp/Cntr=0.3,0.1

Type RM Length L Ch R = 1 ,486     ,127.4,124.1,121.7
XS GIS Cut Line= 2
2165523.54640485328147.6936964152165480.13002873328496.058087314
#Sta/Elev= 30
       0 1916.82    11.2 1911.93    34.4 1903.83    60.8 1889.72    90.6 1870.29
    97.2 1867.17   107.2 1863.34   126.9 1854.28   130.3  1851.9   140.2 1843.03
     160 1829.96   163.3 1828.79   169.11827.652   173.2 1827.24   179.8 1827.72
   183.2 1828.41   197.8 1834.86   209.6 1839.45   219.5 1841.09   232.7 1841.94
   236.1 1842.77   239.3  1847.2   242.7 1850.45   249.3 1853.84   252.6 1854.89
   285.6 1861.65   308.8 1865.82   318.7 1868.13   345.1 1872.16   351.1 1872.42
#Mann= 4 ,-1 , 0
       0      .1       0   169.1    .045       0   179.8      .1       0
  245.59     .06       0
Bank Sta=169.1,179.8
XS Rating Curve= 0 ,0
Exp/Cntr=0.3,0.1

Type RM Length L Ch R = 1 ,362     ,135.3,136.3,135.1
XS GIS Cut Line= 2
 2165354.4161203328253.1721659292165446.56567451328553.108353222
#Sta/Elev= 30
       0 1839.86     4.3 1838.87     7.7 1837.73    11.1 1836.25    21.4 1830.96
    28.3 1829.09    31.7 1829.17      42  1830.2    45.5 1830.29    48.9 1829.86
    66.1 1823.65    75.91822.369    83.4 1821.79    90.1    1822    93.5  1822.4
   103.8 1825.08   110.7 1826.48     145 1836.63   149.1 1838.03   162.2 1843.53
   173.5 1847.58   189.6 1851.57   203.3 1853.74   234.2 1857.26   254.8 1858.91
   265.1 1859.46   278.9 1859.08   299.4 1857.94   309.7  1856.1   313.8 1855.61
#Mann= 3 , 0 , 0
       0      .1       0    75.9    .045       0    93.5      .1       0
Bank Sta=75.9,93.5
XS Rating Curve= 0 ,0
Exp/Cntr(USF)=0,0
Exp/Cntr=0.3,0.1

Type RM Length L Ch R = 1 ,225     ,60.3,61.2,61.7
XS GIS Cut Line= 2
2165255.91740853328322.6185624082165339.82292163 328640.06404871
#Sta/Elev= 30
       0 1822.44     7.1 1821.84    20.6 1821.39      41 1822.88    47.8 1822.92
      58 1821.62    61.4 1820.49    64.7 1818.91    68.8  1817.7    74.2 1817.42
    82.2 1817.88    89.91817.631   102.1 1817.21   106.21817.668   109.1 1817.98
   115.7 1817.85   122.7 1818.78   148.3 1818.92   156.4 1820.62   162.7 1822.49
   170.8  1823.5   227.6 1822.38   241.2 1822.68   262.1 1821.56   281.9 1822.13
   295.5 1824.11   298.9 1824.23   305.7 1824.12   313.1 1823.27   328.3 1823.25
#Mann= 3 , 0 , 0
       0      .1       0    89.9    .045       0   106.2      .1       0
Bank Sta=89.9,106.2
XS Rating Curve= 0 ,0
Exp/Cntr(USF)=0,0
Exp/Cntr=0.3,0.1

Type RM Length L Ch R = 1 ,164     ,116.5,115.7,114.8
XS GIS Cut Line= 2
2165204.14345572 328358.685661162165274.45354427328617.566780397
#Sta/Elev= 30
       0 1819.11    10.5 1819.41    20.7 1820.47    27.5 1820.94    44.5 1820.79
    47.9 1820.34    49.3 1819.79    51.3 1818.82    54.7 1816.45    57.71814.865
    61.5 1814.12    64.9 1814.19    68.3 1814.99    75.1  1817.1    78.5 1817.37
      92 1817.19   102.3 1817.67   110.9 1817.64   115.9 1817.34   122.7 1816.51
   132.1 1816.35   149.9 1817.28   166.9 1816.97   180.3 1817.11   187.3 1818.78
   190.9 1819.96   196.3  1821.1   207.7 1822.03   234.9 1821.36   268.3 1821.18
#Mann= 3 , 0 , 0
       0      .1       0    57.7    .045       0    68.3      .1       0
#XS Ineff= 2 , 0
                          149.32         1820.16
Permanent Ineff=
       F       F
Bank Sta=57.7,68.3
XS Rating Curve= 0 ,0
Exp/Cntr(USF)=0,0
Exp/Cntr=0.3,0.1

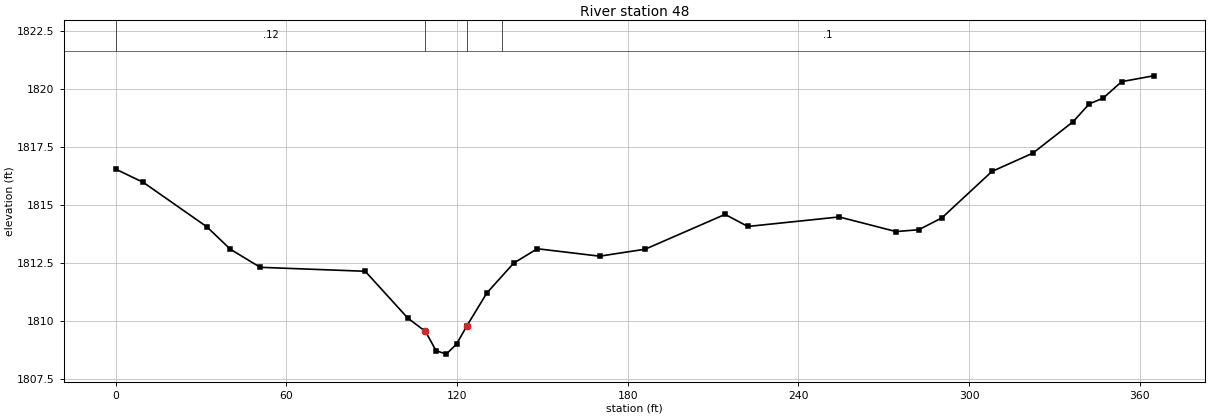
Type RM Length L Ch R = 1 ,48      ,48,48,48
XS GIS Cut Line= 4
2165121.02277375328348.568219189 2165103.4260943328434.456773637
2165122.27967942328478.0295036982165254.33082947328665.977675053
#Sta/Elev= 30
       0 1816.55     9.7 1815.98      32 1814.07    40.3  1813.1    50.8 1812.32
    87.7 1812.15   102.7 1810.13   108.91809.557   112.6 1808.73   116.2 1808.58
   119.8 1809.01   123.4 1809.79   130.5 1811.22   139.9  1812.5   148.2 1813.12
   170.1  1812.8   186.1  1813.1   214.2  1814.6   222.2 1814.08   254.3 1814.49
   274.3 1813.86   282.3 1813.94   290.4 1814.45     308 1816.45   322.4 1817.24
   336.5 1818.59   342.2 1819.36   347.1 1819.61   353.6 1820.32   364.8 1820.57
#Mann= 4 ,-1 , 0
       0     .12       0   108.9    .045       0   123.4     .12       0
  135.65      .1       0
Bank Sta=108.9,123.4
XS Rating Curve= 0 ,0
Exp/Cntr=0.3,0.1
LCMann Table=0

Chan Stop Cuts=-1
Use User Specified Reach Order=0
Composite Channel Slope=5